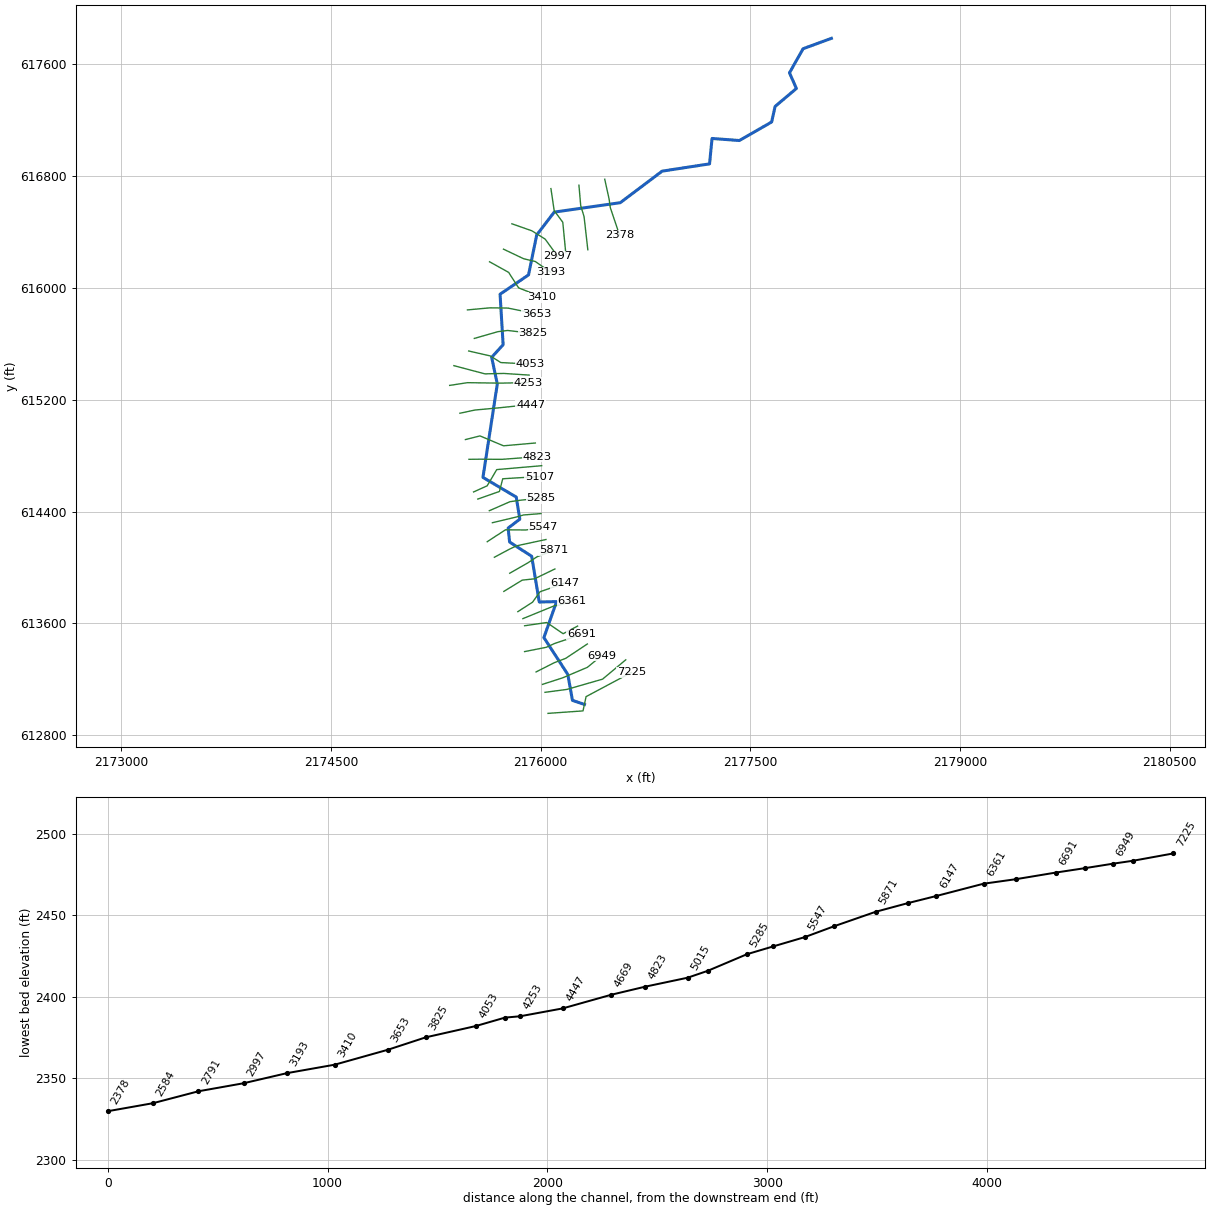
--- DEVILFK.prj (project) ---

Proj Title=DEVILFK
Current Plan=p01
Default Exp/Contr=0,0
English Units
Geom File=g01
Flow File=f01
Plan File=p01
Background Map Layer=Inundation Boundary (P100yr Value_0)
BEGIN DESCRIPTION:
----------MODEL BY WOOD PLC 2022----------
AFH study
Randolph County, WV
HEC-RAS Version: RAS 6.2
Vertical Datum: NAVD88
Projection: NAD 1983 StatePlane West Virginia S FIPS 4702 (US Feet)
Terrain: 1-meter LIDAR (FEMA Region III 3DEP collected 2016-2018)
Land Use: 2019 NLCD
Hydrologic Method:
WV SIR2010-5033 regression equations
Additional Model Notes:
None
END DESCRIPTION:
DSS Export Rating Curves= 0
DSS Export Rating Curve Sorted= 0
DSS Export Volume Flow Curves= 0
DXF OffsetX= 0
DXF OffsetY= 0
DXF ScaleX= 0
DXF ScaleY= 0

--- DEVILFK.p01 (plan) ---

Plan Title=Floodplain
Program Version=6.20
Short Identifier=Floodplain
Geom File=g01
Flow File=f01
Subcritical Flow
K Sum by GR= 0
Std Step Tol= 0.01
Critical Tol= 0.01
Num of Std Step Trials= 20
Max Error Tol= 0.3
Flow Tol Ratio= 0.001
Split Flow NTrial= 30
Split Flow Tol= 0.02
Split Flow Ratio= 0.02
Log Output Level= 0
Friction Slope Method= 1
Unsteady Friction Slope Method= 2
Unsteady Bridges Friction Slope Method= 1
Parabolic Critical Depth
Global Vel Dist= 0 , 0 , 0
Global Log Level= 0
CheckData=True
Encroach Param=-1 ,0,0, 0
Mapping Interval=1HOUR
Computation Time Step Use Courant=        0
Computation Time Step Use Time Series=    0
Computation Time Step Count To Double=0
Computation Time Step Max Doubling=0
Computation Time Step Max Halving=0
Computation Time Step Residence Courant=0
Run HTab= 0
Run UNet= 0
Run Sediment= 0
Run PostProcess= 0
Run WQNet= 0
Run RASMapper=-1
UNET Theta= 0
UNET Theta Warmup= 0
UNET ZTol= 0
UNET ZSATol= 0
UNET MxIter= 0
UNET Max Iter WO Improvement= 0
UNET MaxInSteps= 0
UNET DtIC= 0
UNET DtMin= 0
UNET MaxCRTS= 0
UNET WFStab= 0
UNET SFStab= 0
UNET WFX= 1
UNET SFX= 1
UNET Gravity=32.174
UNET 1D Methodology=Finite Difference
UNET DSS MLevel= 1
UNET Pardiso=0
UNET DZMax Abort= 0
UNET Use Existing IB Tables= 0
UNET Froude Reduction=False
UNET Froude Limit= 0
UNET Froude Power= 0
UNET D1 Cores= 0
UNET WindReference=Eulerian
UNET WindDragFormulation=Hsu (1988)
UNET D2 Coriolis=0
UNET D2 Cores= 0
UNET D2 Theta= 1
UNET D2 Theta Warmup= 1
UNET D2 Z Tol= 0.01
UNET D2 Volume Tol= 0.01
UNET D2 Max Iterations= 20
UNET D2 Equation= 0
UNET D2 RampUpFraction=0.1
UNET D2 TimeSlices= 1
UNET D2 Turbulence Formulation=Non-Conservative (original)
UNET D2 Eddy Viscosity=0.3
UNET D2 Transverse Eddy Viscosity=0.1
UNET D2 Smagorinsky Mixing=0
UNET D2 BCVolumeCheck=0
UNET D2 Cores=0
UNET D2 SolverType=PARDISO (Direct)
UNET D2 Minimum Iterations= 2147483647
UNET D2 Maximum Iterations= 2147483647
UNET D2 Restart Number= 10
UNET D2 Relaxation Coeff=1.3
UNET D2 SOR Precondition Iterations= 10
UNET D2 ILUT Maximum Fill= 8
UNET D2 ILUT Tolerance=1E-08
UNET D1D2 MaxIter= 0
UNET D1D2 ZTol=0.01
UNET D1D2 QTol=0.1
UNET D1D2 MinQTol=1
Write IC File= 0
Write IC File at Fixed DateTime=0
Write IC File at Sim End=0
Echo Input=False
Echo Parameters=False
Echo Output=False
Write Detailed= 0
HDF Write Warmup=0
HDF Write Time Slices=0
HDF Flush=0
HDF Compression= 1
HDF Chunk Size= 1
HDF Spatial Parts= 1
HDF Use Max Rows=0
HDF Fixed Rows= 1
Calibration Method= 0
Calibration Iterations= 20
Calibration Max Change=0.05
Calibration Tolerance=0.2
Calibration Maximum=1.5
Calibration Minimum=0.5
Calibration Optimization Method= 1
WQ AD Non Conservative
WQ ULTIMATE=-1
WQ Max Comp Step=1HOUR
WQ Output Interval=15MIN
WQ Output Selected Increments= 0
WQ Output face flow=0
WQ Output face velocity=0
WQ Output face area=0
WQ Output face dispersion=0
WQ Output cell volume=0
WQ Output cell surface area=0
WQ Output cell continuity=0
WQ Output cumulative cell continuity=0
WQ Output face conc=0
WQ Output face dconc_dx=0
WQ Output face courant=0
WQ Output face peclet=0
WQ Output face adv mass=0
WQ Output face disp mass=0
WQ Output cell mass=0
WQ Output cell source sink temp=0
WQ Output nsm pathways=0
WQ Output nsm derived pathways=0
WQ Create Restart=0
WQ Fixed Restart=0
WQ System Summary=0
WQ Write To DSS=0
Sorting and Armoring Iterations= 10
XS Update Threshold= 0.02
Bed Roughness Predictor= 0
Hydraulics Update Threshold= 0.02
Energy Slope Method= 1
Volume Change Method= 1
Sediment Retention Method= 0
Sediment TS Multiplier= 1
Warm Up Method= 0
XS Weighting Method= 0
Number of US Weighted Cross Sections= 1
Number of DS Weighted Cross Sections= 1
Upstream XS Weight=0
Main XS Weight=1
Downstream XS Weight=0
Number of DS XS's Weighted with US Boundary= 1
Upstream Boundary Weight= 1
Weight of XSs Associated with US Boundary= 0
Number of US XS's Weighted with DS Boundary= 1
Downstream Boundary Weight= 0.5
Weight of XSs Associated with DS Boundary= 0.5
Percentile Method= 0
Sediment Output Level= 3
Mass or Volume Output= 0
Output Increment Type= 1
Profile and TS Output Increment= 1
Transport Output Increment 1
XS Output Flag= 0
XS Output Increment= 10
Read HDF5 Sediment Hotstart= 0
Sediment Hotstart Type= 0
Write Gradation File= 0
Read Gradation Hotstart= 0
Write HDF5 File= 1
Write Binary Output= 1
Write DSS Sediment File= 0
DSS Sediment Output Type= 1
SV Curve= 0
Specific Gage Flag= 0
Subcell Erosion Methods= 0
Subcell Deposition Methods= 0
Advection Scheme= 1
Matrix Solver= 0
Implicit Weighting Factor= 1
Maximum Outer Loop Convergence Iterations= 5
Convergence Maximum Absolute= 0.001
Convergence RMSE= 0.0001
Grain Fractions Max Abs Error= 0.001
Max Subgrid Regions= 1
Max Subgrid Length Scale= 3.402823E+38
Initial Layer Thickness= 3.402823E+38
Min Layer Thickness= 3.402823E+38
Max Layer Thickness= 3.402823E+38
Number of Layers= 5

--- DEVILFK.f01 (steady flow) ---

Flow Title=Flow
Program Version=6.20
Number of Profiles= 1
Profile Names=P100yr
River Rch & RM=DEVILFK,Main,7225
     478
River Rch & RM=DEVILFK,Main,2997
     541
Boundary for River Rch & Prof#=DEVILFK,Main            , 1
Up Type= 0
Dn Type= 3
Dn Slope=0.05004
DSS Import GetInterval= 0
DSS Import GetPeak= 0
DSS Import FillOption= 0

--- DEVILFK.g01 (geometry) ---

Geom Title=Geometry
Program Version=6.20

River Reach=DEVILFK         ,Main
Reach XY= 30
2176314.40736003613019.8567232932176228.43645014613049.052531934
     2176195.141      613234.689     2176024.134      613498.144
     2176114.846      613755.5232175991.14207114613752.673926603
2175936.62625716614080.000290258     2175778.908      614181.738
2175768.38934059614281.461475028     2175851.825      614345.367
     2175826.217      614503.352     2175588.196      614643.977
       2175690.8      615312.2072175650.41588264615503.072194854
     2175732.467      615592.936     2175710.592      615954.394
     2175914.238      616092.415     2175972.571      616377.832
     2176098.092      616541.894     2176570.488      616609.082
2176870.05673751616834.740531356     2177209.093      616886.672
2177226.91333815      617068.4332177422.21617662617053.774677904
2177653.18943961617186.2909824052177677.90358006617297.437055314
     2177830.249      617425.9682177780.82880651617537.957311222
2177878.02648989617710.305192195     2178080.661      617784.689

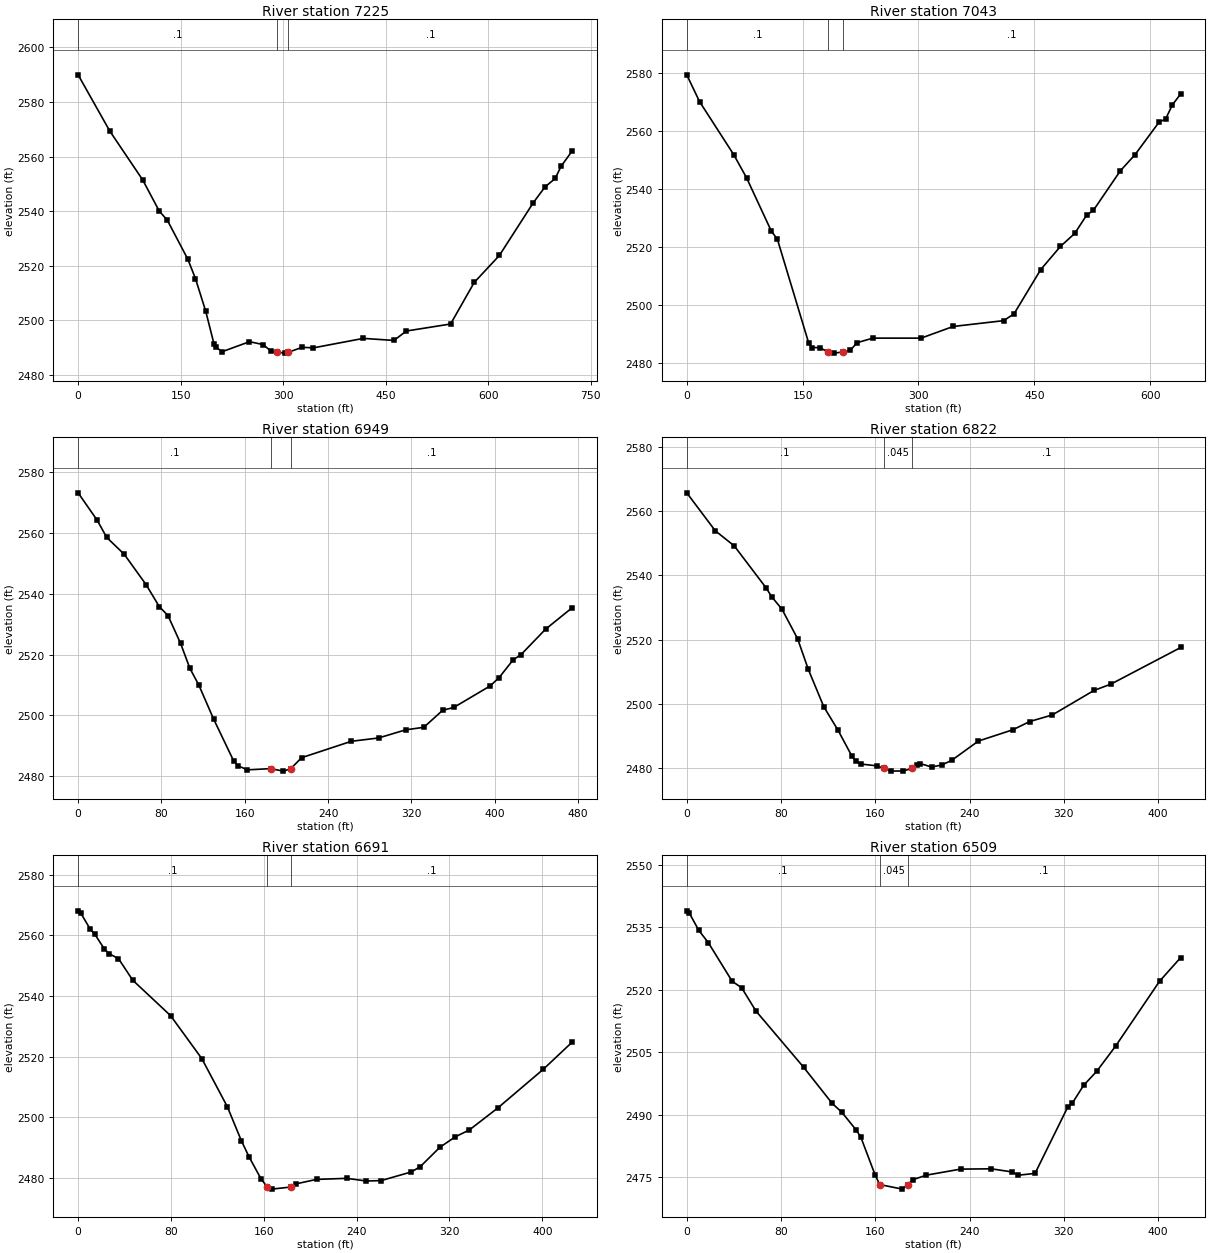
Type RM Length L Ch R = 1 ,7225    ,190.3,182.4,170.7
XS GIS Cut Line= 4
 2176053.8653973612956.1100542572176303.93869758612973.803919843
2176325.84355573 613075.900072192176650.09373989613248.804314368
#Sta/Elev= 30
       0 2589.98    46.4 2569.35    94.5 2551.47   118.6  2540.1   130.5 2536.72
   160.5 2522.42   171.7  2515.3   186.7 2503.34   198.8 2491.37   201.6 2490.16
   210.8 2488.55   250.7 2492.21   270.4 2491.17   282.8 2488.65     291 2488.35
   303.2 2488.02   307.72488.349   327.7 2490.15   344.2 2489.95   417.3 2493.42
     462 2492.67   480.2 2496.12   544.9 2498.69   579.5 2513.94   616.2 2523.79
     666 2543.18     683  2548.9   697.9 2552.01   706.4 2556.42   722.6 2562.05
#Mann= 3 ,-1,0
       0      .1       0     291    .045       0   307.7      .1       0
Bank Sta=291,307.7
XS Rating Curve= 0 ,0
Exp/Cntr(USF)=0,0
Exp/Cntr=0.3,0.1

Type RM Length L Ch R = 1 ,7043    ,92.1,93.4,94.4
XS GIS Cut Line= 4
2176031.80536639 613106.631436032176188.22341892613127.425366881
2176443.75874551613200.8983305532176609.56267087613339.221901461
#Sta/Elev= 30
       0 2579.38    16.5 2570.19    60.9 2551.86    77.4 2543.94   109.4 2525.62
   117.4 2522.72   157.7 2487.19   161.9 2485.45   172.1 2485.45   182.7 2483.96
     191 2483.54   202.92483.961   211.9 2484.58   220.6 2487.14     241 2488.71
   303.4  2488.7     345 2492.72   410.2 2494.72   423.7 2497.03   458.3  2512.3
   483.8 2520.27   502.4 2524.77   517.9 2531.11   526.4 2532.67   561.5 2546.35
   580.4 2551.87   611.4 2563.03   620.1 2564.19   628.7    2569   639.6 2572.83
#Mann= 3 ,-1,0
       0      .1       0   182.7    .045       0   202.9      .1       0
Bank Sta=182.7,202.9
XS Rating Curve= 0 ,0
Exp/Cntr=0.3,0.1

Type RM Length L Ch R = 1 ,6949    ,127.6,127.4,125.7
XS GIS Cut Line= 4
2176014.04188252 613163.578046712176157.64845123613210.051056802
2176335.63091631613285.7218571832176435.85664442613368.323641905
#Sta/Elev= 30
       0 2573.19    18.2 2564.23    27.5 2558.51    44.3 2552.98    65.3 2542.98
    77.9  2535.8    86.3 2532.81    98.3 2523.75   107.3 2515.47   115.8 2510.05
     130 2498.87   149.4 2484.99   153.7 2483.44   162.4 2482.11   184.72482.506
   197.1 2481.69  204.052482.459   214.5  2486.1   262.3  2491.5   288.4 2492.59
   314.5 2495.27   331.9  2496.1     350  2501.7   360.6 2502.62   395.5 2509.69
     404 2512.38   417.6 2518.26   425.2    2520   448.7 2528.34   474.2 2535.39
#Mann= 3 ,-1,0
       0      .1       0   184.7    .045       0  204.05      .1       0
Bank Sta=184.7,204.05
XS Rating Curve= 0 ,0
Exp/Cntr=0.3,0.1

Type RM Length L Ch R = 1 ,6822    ,130,130.9,132.5
XS GIS Cut Line= 4
2175968.23598703 613252.520789262176098.36747559613318.574763302
 2176180.1974816613349.7480989252176334.79734207613452.590173238
#Sta/Elev= 30
       0 2565.74    24.2 2553.91    40.3  2549.2    67.2 2536.17    72.2 2533.28
    80.8 2529.45    94.1 2520.22   103.1 2510.73   116.3 2499.03   128.4  2491.7
   140.3 2483.53   143.5 2482.05   147.9 2481.17   161.8 2480.59  167.172479.785
   173.6 2478.96   183.5 2479.03  191.452479.785     195 2480.99   198.2 2481.31
   207.8 2480.24   216.4 2480.87   224.9 2482.34   247.5 2488.34   276.7 2491.85
   291.1 2494.43   310.3 2496.49   345.6 2504.12     360  2506.1   419.2 2517.51
#Mann= 3 ,-1,0
       0      .1       0  167.17    .045       0  191.45      .1       0
Bank Sta=167.17,191.45
XS Rating Curve= 0 ,0
Exp/Cntr(USF)=0,0
Exp/Cntr=0.3,0.1

Type RM Length L Ch R = 1 ,6691    ,195,182.3,174.4
XS GIS Cut Line= 4
2175886.00780429613398.000990611 2176040.8362702613428.790798292
2176101.64024288613456.402043484 2176292.1053144613520.923831786
#Sta/Elev= 30
       0 2568.14     2.2 2567.44    10.4 2562.12    14.4  2560.4    22.6 2555.56
    26.7    2554    34.8 2552.36    47.1 2545.23    79.7 2533.54   106.6 2519.36
   128.6 2503.49   140.6 2492.33   147.4 2486.87   157.6  2479.7  163.022476.975
   166.7 2476.28  183.472476.975   187.8 2478.02   205.5 2479.49   231.5 2479.84
   248.4 2478.96   261.1 2479.09   287.2 2481.96   294.9 2483.71   311.8  2490.1
     325 2493.54   337.1 2495.79   361.6 2503.04   400.8  2515.8   425.7 2524.78
#Mann= 3 ,-1,0
       0      .1       0  163.02    .045       0  183.47      .1       0
Bank Sta=163.02,183.47
XS Rating Curve= 0 ,0
Exp/Cntr=0.3,0.1

Type RM Length L Ch R = 1 ,6509    ,137.7,147.3,153.2
XS GIS Cut Line= 4
2175886.08716491613582.824991495 2176044.6342103613606.067999264
2176161.62883131613525.8326176352176265.10652163613580.495064648
#Sta/Elev= 30
       0 2538.92     2.1 2538.41    10.2 2534.24    18.3 2531.29    38.5 2522.04
    46.6 2520.46    58.7  2514.9    99.1 2501.44   123.4 2492.75   131.5 2490.65
   143.6 2486.43   147.6 2484.72   159.8 2475.61  163.732473.298     183  2472.2
   187.42473.298   192.2  2474.5   203.3 2475.55   232.4    2477   258.4 2477.07
   275.6 2476.34   281.4 2475.54   295.5 2475.97   323.1 2491.79   327.2 2492.85
   336.7 2497.07   347.9 2500.47   363.8 2506.47   401.2 2522.06   419.1 2527.72
#Mann= 3 ,-1,0
       0      .1       0  163.73    .045       0   187.4      .1       0
Bank Sta=163.73,187.4
XS Rating Curve= 0 ,0
Exp/Cntr=0.3,0.1

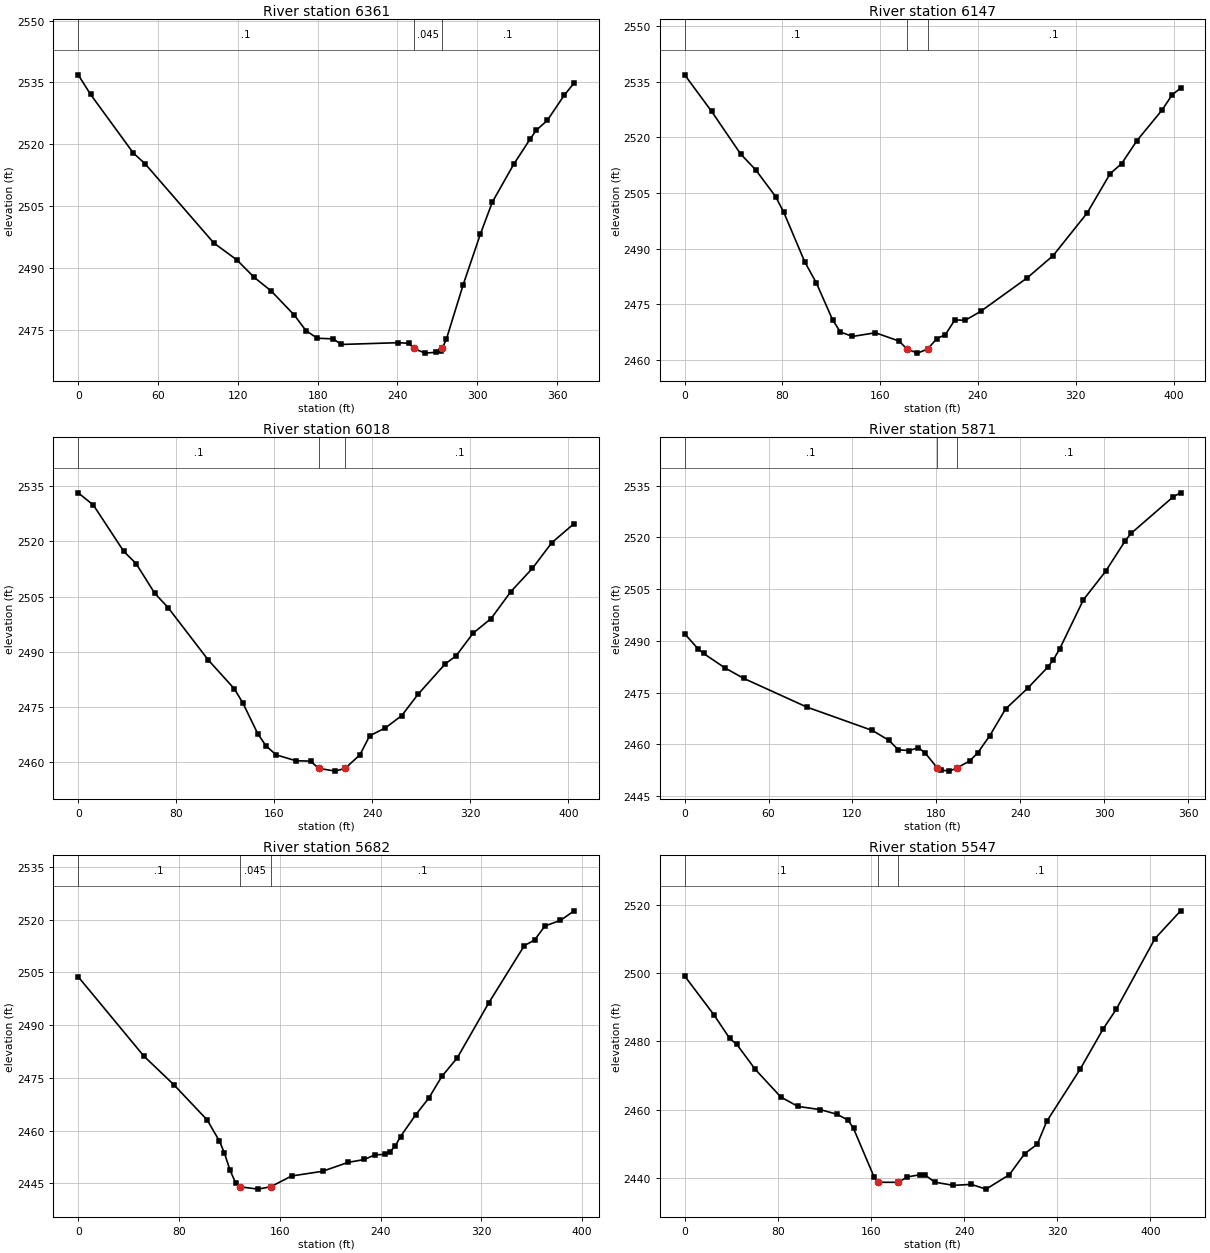
Type RM Length L Ch R = 1 ,6361    ,198.1,214.5,217.4
XS GIS Cut Line= 4
2175873.72810186 613633.64739976  2176100.446009 613726.40288551
2176134.95188975613730.1962121032176223.24862072 613759.96584978
#Sta/Elev= 30
       0 2536.84     9.3 2532.09    41.5 2517.87    50.2 2515.32     102 2496.09
   119.3    2492   132.3 2487.78   145.3 2484.42   162.6 2478.58   171.2 2474.88
   179.8 2473.02   191.7 2472.88   197.8 2471.52   240.7 2471.95   248.7  2471.8
  252.332470.542   260.8 2469.42   268.8 2469.62   272.9 2469.99  273.662470.543
   276.9 2472.88   289.4 2485.92   302.3 2498.18   311.4 2506.02   327.4 2515.14
   339.8 2521.28   344.3 2523.38   352.7  2525.8   365.4 2531.88   372.9 2534.87
#Mann= 3 ,-1,0
       0      .1       0  252.33    .045       0  273.66      .1       0
Bank Sta=252.33,273.66
XS Rating Curve= 0 ,0
Exp/Cntr=0.3,0.1

Type RM Length L Ch R = 1 ,6147    ,137.3,129.4,121.3
XS GIS Cut Line= 4
2175837.66607907613683.5738726912175943.08989388613751.574888003
2175996.40319353613826.0824407372176174.61024587613888.105065179
#Sta/Elev= 30
       0 2536.82      22 2526.99    45.8  2515.5      58 2511.28    74.4 2504.04
    81.1  2499.8    98.2  2486.5   107.7 2480.81     121 2470.88   127.4 2467.58
   137.3 2466.38   156.1 2467.37   175.4 2465.14  181.942462.977   190.5 2461.89
  198.752462.975   206.1 2465.72   213.4  2466.9   221.1 2470.85   229.5 2470.72
   242.2 2473.13   280.4 2482.19   301.5 2488.15   329.3 2499.61   348.1 2510.19
   357.6 2512.94   370.1 2519.12   390.5 2527.29   398.9 2531.46   405.8 2533.22
#Mann= 3 ,-1,0
       0      .1       0  181.94    .045       0  198.75      .1       0
Bank Sta=181.94,198.75
XS Rating Curve= 0 ,0
Exp/Cntr=0.3,0.1

Type RM Length L Ch R = 1 ,6018    ,143.4,146.3,148
XS GIS Cut Line= 4
2175737.64581813613828.5125922842175869.47648809613909.430388032
2175956.76917204613918.4767982482176102.86078276 613989.08774343
#Sta/Elev= 30
       0 2533.22    12.4 2529.88    37.2 2517.28    47.2 2513.99    62.4 2505.92
    73.4 2501.97   106.2 2487.72   127.4 2479.91   134.4 2476.03   146.6 2467.64
   153.2 2464.41   161.4 2461.97   177.5 2460.35   189.6 2460.24  196.162458.284
   209.7 2457.52  217.882458.285   229.9 2461.95   237.8 2467.12   250.7 2469.29
     264 2472.62   277.3 2478.42   299.5 2486.69   308.4 2488.89   322.2 2495.03
   336.9 2499.01   352.9 2506.29   370.6 2512.67   386.5 2519.67   404.7 2524.86
#Mann= 3 ,-1,0
       0      .1       0  196.16    .045       0  217.88      .1       0
Bank Sta=196.16,217.88
XS Rating Curve= 0 ,0
Exp/Cntr(USF)=0,0
Exp/Cntr=0.3,0.1

Type RM Length L Ch R = 1 ,5871    ,187.7,189.2,180.2
XS GIS Cut Line= 4
2175779.68137473613958.4466626992175911.71451223614034.184406272
2175975.37076233614076.4691947012176093.06039445 614121.78804063
#Sta/Elev= 30
       0 2492.03     9.8 2487.55    13.5 2486.33    28.7 2482.16    42.1 2479.12
    87.3 2470.79   134.3 2463.99     146 2461.16   152.8 2458.38   160.5 2458.18
   167.2 2458.99     172 2457.48  180.612453.156   183.6 2452.51   189.3 2452.21
  194.782453.156   203.8 2455.15   209.5 2457.46   218.2 2462.48   229.5 2470.22
   245.3 2476.24   259.5 2482.28   263.7  2484.5   268.1 2487.57   285.2  2501.9
     301  2510.1   315.2 2519.05   319.4 2521.18   349.5 2531.77   354.7 2532.89
#Mann= 3 ,-1,0
       0      .1       0  180.61    .045       0  194.78      .1       0
Bank Sta=180.61,194.78
XS Rating Curve= 0 ,0
Exp/Cntr=0.3,0.1

Type RM Length L Ch R = 1 ,5682    ,139.6,134.7,130
XS GIS Cut Line= 4
2175669.90196408614072.9024511142175777.71590875 614130.53945935
2175827.74843504614154.3835641852176038.88354535614199.751533972
#Sta/Elev= 30
       0 2503.77    52.1  2481.2    75.8 2473.08   102.4    2463   112.1 2456.99
     116 2453.63   120.5 2448.68     125 2445.08  128.232444.001   142.7 2443.33
  152.782444.002   169.3 2447.07   193.9 2448.41   214.1 2450.93   227.2 2451.77
   235.4 2453.11   243.6 2453.19   247.7 2454.03   251.8 2455.73   255.8 2458.31
   267.9 2464.51   278.1 2469.17   288.6 2475.42   300.9 2480.73   325.7 2496.27
     354 2512.62   362.2 2514.25   370.4 2518.23   382.7 2519.83   393.6 2522.55
#Mann= 3 ,-1,0
       0      .1       0  128.23    .045       0  152.78      .1       0
Bank Sta=128.23,152.78
XS Rating Curve= 0 ,0
Exp/Cntr=0.3,0.1

Type RM Length L Ch R = 1 ,5547    ,141.7,143.8,140.9
XS GIS Cut Line= 4
2175618.65363498614184.0754142612175749.23131669 614269.14315638
2175895.38996584614267.9156422842176017.94365695614286.220824695
#Sta/Elev= 30
       0 2499.23      25 2487.88    38.7 2480.88    44.8 2479.11    60.6  2471.8
    82.6 2463.66    97.3 2460.91   116.4 2459.97   130.7 2458.61   140.3  2456.9
     145 2454.43   162.8 2440.05  166.372438.604  183.522438.608   191.1 2440.18
   202.4 2440.85   206.8 2440.65   214.8 2438.65   230.8  2437.7     246    2438
   258.8  2436.6   278.8 2440.83     292 2447.03   302.8 2449.79   310.9  2456.5
   339.5 2471.78   359.4 2483.69   370.7  2489.5   403.9 2510.24   425.9 2518.39
#Mann= 3 ,-1,0
       0      .1       0  166.37    .045       0  183.52      .1       0
Bank Sta=166.37,183.52
XS Rating Curve= 0 ,0
Exp/Cntr=0.3,0.1

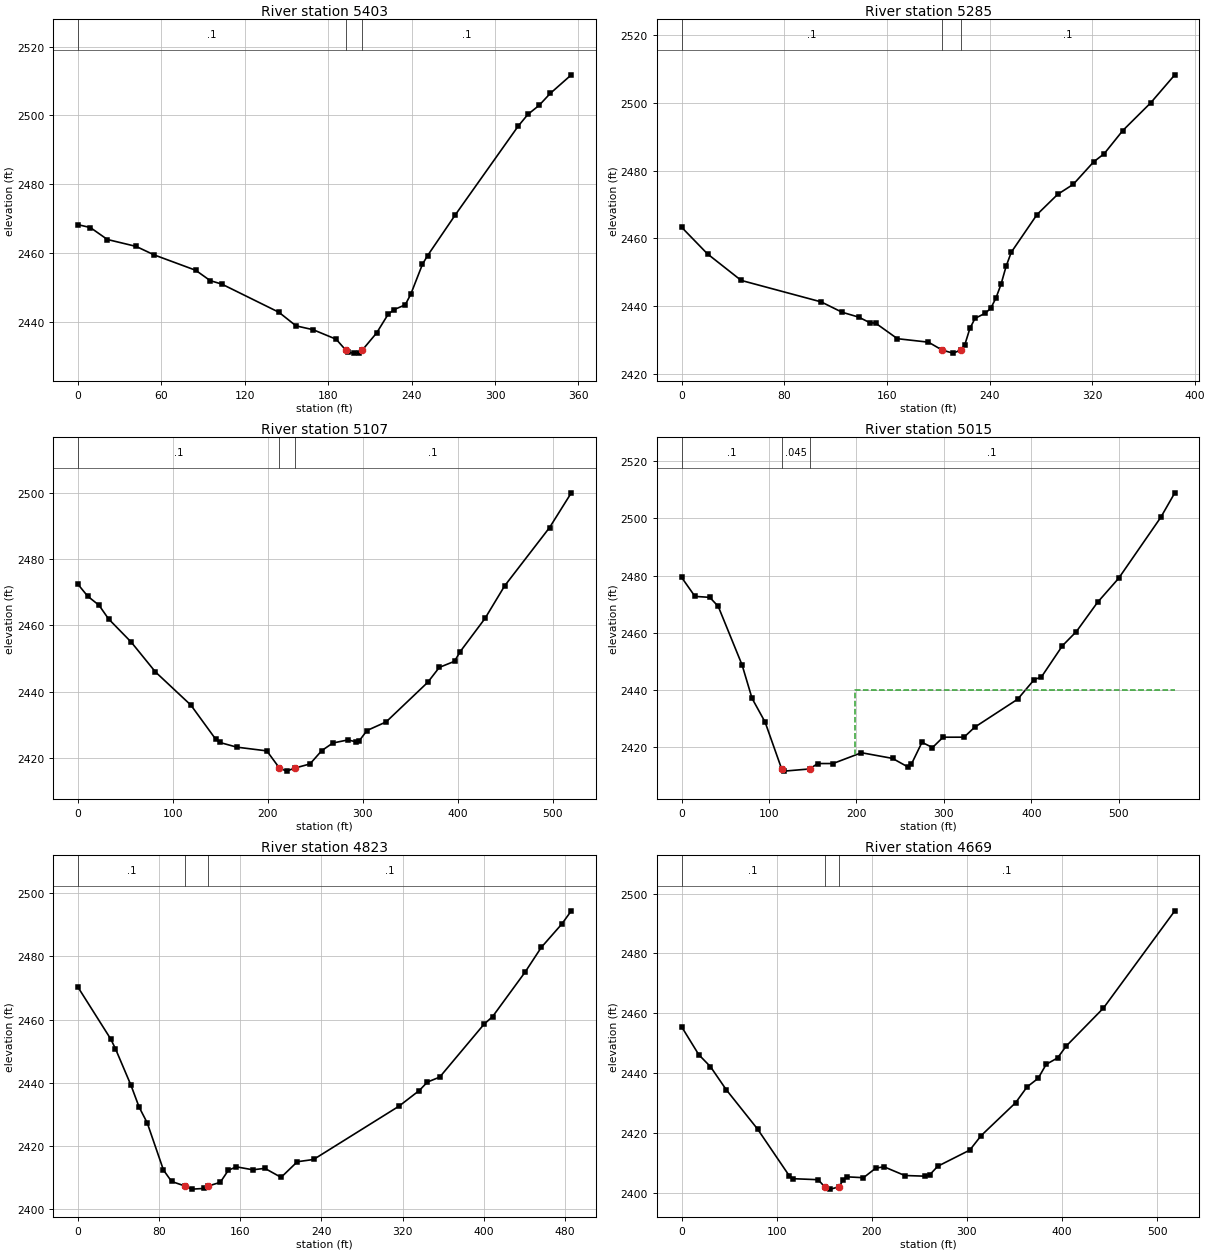
Type RM Length L Ch R = 1 ,5403    ,118.7,118.2,117.2
XS GIS Cut Line= 4
2175655.60704575614319.955503764 2175829.4794865614361.190074692
2175878.54300173614375.4014066342176003.24185227614385.188862385
#Sta/Elev= 30
       0 2468.23     8.8 2467.41    21.1 2463.93    41.7 2461.93    54.7 2459.46
    84.6 2454.99    95.1 2451.97   103.4 2450.97   144.5 2442.78   156.8 2438.83
   169.1 2437.71   185.7 2434.94   192.52431.831     194 2431.11   198.2  2430.9
   202.3 2430.96   204.6 2431.83   214.8 2436.76   223.1  2442.2   227.3 2443.53
   235.4 2444.94   239.4 2448.04   247.8 2456.74   251.5 2459.26   271.5 2471.14
   316.7  2496.9   323.7 2500.32   331.7 2502.91   339.7 2506.38   354.9  2511.8
#Mann= 3 ,-1,0
       0      .1       0   192.5    .045       0   204.6      .1       0
Bank Sta=192.5,204.6
XS Rating Curve= 0 ,0
Exp/Cntr(USF)=0,0
Exp/Cntr=0.3,0.1

Type RM Length L Ch R = 1 ,5285    ,161.4,178.6,180.6
XS GIS Cut Line= 4
2175633.68547541614405.6449610832175781.46079994614470.248996782
2175859.66625854614481.1762590922176002.90529954614495.737519798
#Sta/Elev= 30
       0  2463.3    20.2 2455.42    46.4 2447.61   108.7 2441.27     125 2438.22
     138 2436.77   146.8  2435.1   151.1 2435.01   168.1 2430.41   192.3 2429.38
  203.052427.034   211.4 2426.15  217.532427.033   220.6 2428.59   224.6 2433.47
   228.6  2436.4   236.7 2437.96   240.8 2439.38   244.8 2442.33   248.8 2446.43
   252.8 2451.77   256.8 2455.91   276.9 2467.05     293 2473.01   305.1 2475.95
     321 2482.59   329.2 2484.99   343.7 2491.83   365.4 2499.99   384.2 2508.26
#Mann= 3 ,-1,0
       0      .1       0  203.05    .045       0  217.53      .1       0
Bank Sta=203.05,217.53
XS Rating Curve= 0 ,0
Exp/Cntr=0.3,0.1

Type RM Length L Ch R = 1 ,5107    ,96.4,91.3,84.7
XS GIS Cut Line= 4
 2175551.3251923614489.0343940082175706.18473608614543.498473292
2175729.68706598614634.2918107782175991.07165136614650.310279551
#Sta/Elev= 30
       0 2472.37    10.2  2468.8    22.1 2466.08    32.1 2461.96      56 2454.94
    81.5 2445.93   118.9 2435.89   145.1 2425.56   149.3 2424.61   167.2 2423.19
   198.9 2422.06  212.182416.875   219.7 2415.94  228.542416.874   244.4 2418.11
   256.8 2422.14   268.5 2424.44   284.5 2425.38   292.5 2424.81   296.5 2425.19
   304.5 2428.22   324.6 2430.81   368.5 2442.79   380.7  2447.3   396.7 2449.14
   402.7 2452.07   428.8 2462.08   449.6 2471.97   496.9 2489.58   519.8 2500.07
#Mann= 3 ,-1,0
       0      .1       0  212.18    .045       0  228.54      .1       0
Bank Sta=212.18,228.54
XS Rating Curve= 0 ,0
Exp/Cntr=0.3,0.1

Type RM Length L Ch R = 1 ,5015    ,208.6,192,177.8
XS GIS Cut Line= 5
2175521.17329965 614539.865560542175618.13838158614583.851045739
2175658.60449216614651.6857725882175686.62476327614699.857854631
2176008.25441651614727.691190008
#Sta/Elev= 30
       0 2479.43    15.3 2472.78    32.2 2472.44    41.9  2469.3    69.2 2448.81
    80.6 2437.14    95.5 2428.87  114.442412.491   117.3 2411.73  146.442412.491
   155.6 2414.38   173.1 2414.38   205.7 2418.16   241.2 2416.18   258.8 2413.19
   262.8 2414.17   274.9  2421.8   286.9 2419.96     299 2423.58     323 2423.59
   335.1 2427.06   384.3 2436.86   403.3 2443.73   411.4  2444.6   435.5 2455.54
   451.5 2460.51   475.6 2470.69   499.7 2479.07   547.9 2500.37     564 2508.96
#Mann= 3 ,-1,0
       0      .1       0  114.44    .045       0  146.44      .1       0
#XS Ineff= 2 , 0
                          197.98         2439.93
Permanent Ineff=
       F       F
Bank Sta=114.44,146.44
XS Rating Curve= 0 ,0
Exp/Cntr(USF)=0,0
Exp/Cntr=0.3,0.1

Type RM Length L Ch R = 1 ,4823    ,156.3,154.8,149.1
XS GIS Cut Line= 4
2175487.96822185614773.4318032732175570.46806042614774.354723071
2175721.69644382614773.1173115352175973.63814447614791.750052318
#Sta/Elev= 30
       0 2470.19    32.2 2453.82    36.9 2450.71    52.2 2439.14    60.2 2432.24
    68.2 2427.24    84.2 2412.31    92.2 2408.69  105.852407.198   112.2 2406.26
   124.2 2406.47  127.792407.198   140.2 2408.41   148.2 2412.25   156.2 2413.32
   172.2 2412.39   184.2 2412.84   200.2 2409.99   216.2 2414.94   232.2 2415.65
   316.4 2432.53   336.5 2437.51   344.5 2440.19   356.6 2441.75   400.4 2458.54
   408.7  2460.9   440.8 2475.01   456.8 2482.86   476.9 2490.21   486.4 2494.44
#Mann= 3 ,-1,0
       0      .1       0  105.85    .045       0  127.79      .1       0
Bank Sta=105.85,127.79
XS Rating Curve= 0 ,0
Exp/Cntr=0.3,0.1

Type RM Length L Ch R = 1 ,4669    ,218,221.5,226.4
XS GIS Cut Line= 4
 2175462.6636288614914.5842965182175566.90632253614940.782448694
2175735.26657535614870.0299907642175962.98429835614890.129259421
#Sta/Elev= 30
       0 2455.53    18.1 2446.18    30.4 2442.17    46.9 2434.52    79.9 2421.35
   113.2 2405.77   117.5 2404.77   143.6 2404.44  150.422402.087   156.6 2401.29
  165.962402.088   169.6 2404.33   173.9 2405.39   191.3 2405.11   204.3 2408.32
     213 2408.73   234.7 2405.84   256.4 2405.61   260.9 2406.06   269.4 2408.93
   303.1 2414.33   315.1 2419.18   351.3 2430.15   363.3 2435.42     375 2438.29
   383.4 2442.95   395.4  2445.1   404.5 2449.06   443.6 2461.73   518.7 2494.22
#Mann= 3 ,-1,0
       0      .1       0  150.42    .045       0  165.96      .1       0
Bank Sta=150.42,165.96
XS Rating Curve= 0 ,0
Exp/Cntr=0.3,0.1

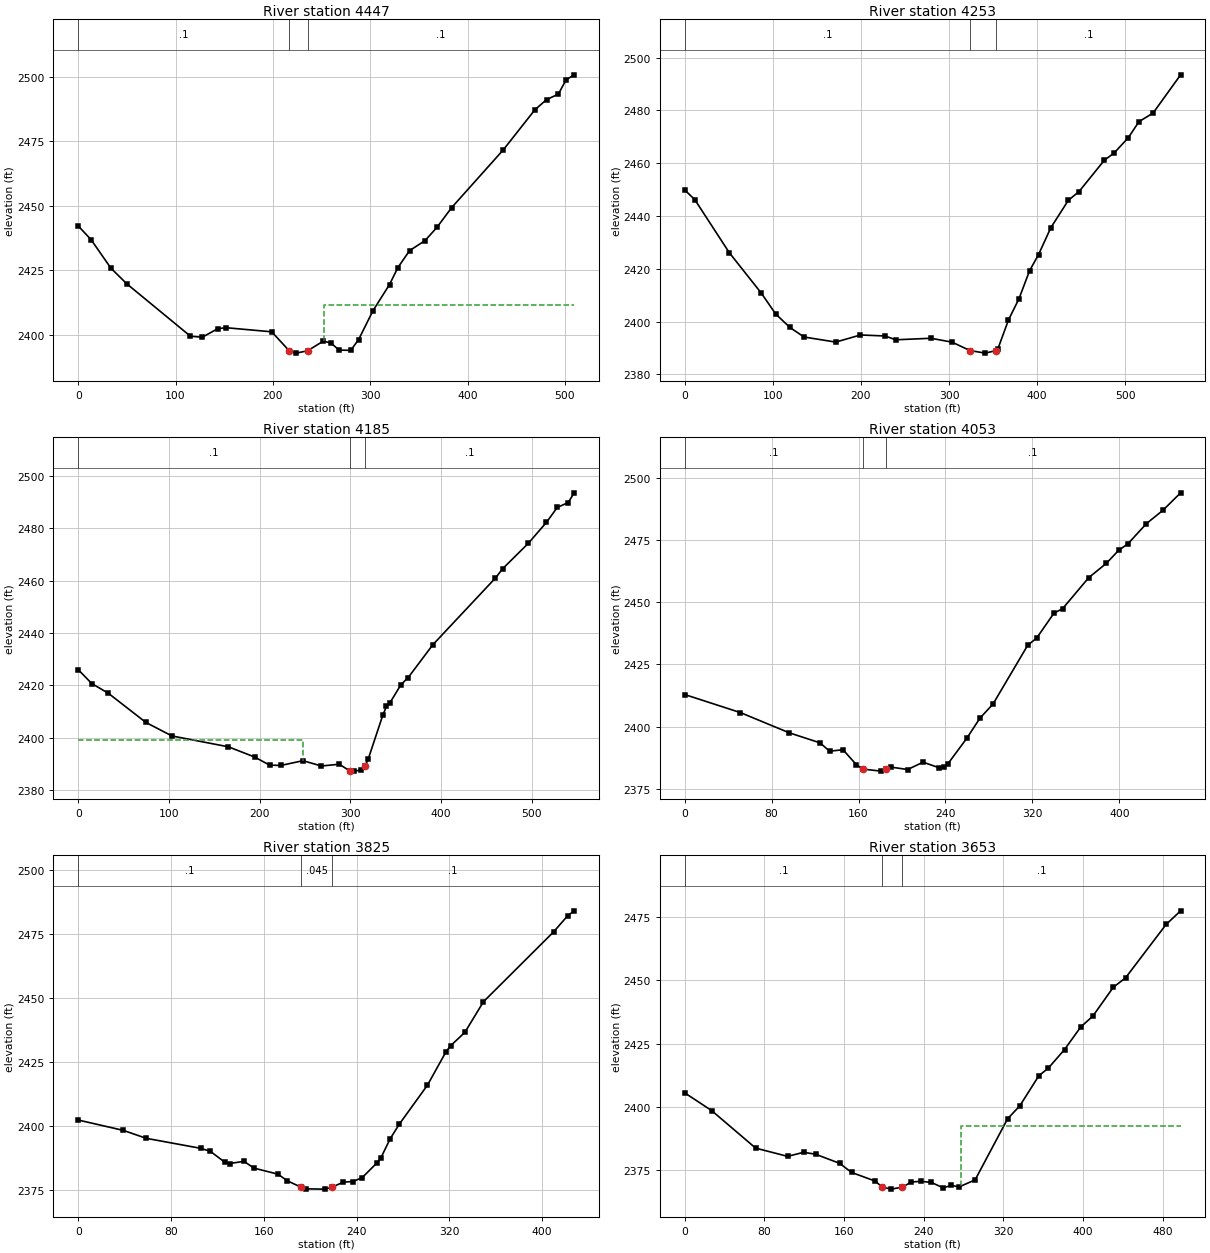
Type RM Length L Ch R = 1 ,4447    ,191.8,193.6,192.6
XS GIS Cut Line= 4
2175423.28627504615102.9333457562175530.62480671615125.876744346
2175704.17683908615141.9073691272175928.44824226615165.282126722
#Sta/Elev= 30
       0 2442.23    13.2 2436.91    33.6 2425.84    49.8 2419.81   115.3 2399.45
   127.4 2399.05   143.2 2402.34   151.5 2402.76   198.8 2401.16  216.862393.771
   223.8 2392.89   235.6 2393.79   251.9 2397.57   259.9 2396.74     268 2394.06
     280 2393.97   288.1 2398.17   302.8 2409.34   319.8 2419.48   328.3    2426
   340.4 2432.64   356.4 2436.57   368.5 2441.65   383.6 2449.31   436.9 2471.83
     469 2487.21   481.1 2491.23   493.2 2493.33   501.2 2498.88   509.5 2500.84
#Mann= 3 ,-1,0
       0      .1       0  216.86    .045       0   235.6      .1       0
#XS Ineff= 2 , 0
                          252.41         2411.59
Permanent Ineff=
       F       F
Bank Sta=216.86,235.6
XS Rating Curve= 0 ,0
Exp/Cntr=0.3,0.1

Type RM Length L Ch R = 1 ,4253    ,67.5,68.6,69.6
XS GIS Cut Line= 4
 2175350.1684083615302.0963224852175477.36103153615321.682354727
2175708.00282677 615318.358719872175911.53476208615321.878889184
#Sta/Elev= 30
       0 2449.88    11.5  2446.2    50.6 2426.13      87 2410.79   103.2 2402.93
   119.4  2397.8   135.5 2394.17   171.5 2392.25   199.5 2394.95   227.5 2394.56
   239.5 2393.12   279.5  2393.7   303.5 2392.22  323.832389.049     341 2388.07
  353.632389.049   355.5 2389.68   367.5 2400.62   379.5 2408.72   391.5 2419.32
   401.6 2425.36   415.5 2435.52   435.5 2445.97   447.5 2449.23   476.3 2461.12
   487.5  2463.9   503.6 2469.69   515.6 2475.75   531.6 2478.98   562.9 2493.48
#Mann= 3 ,-1,0
       0      .1       0  323.83    .045       0  353.63      .1       0
Bank Sta=323.83,353.63
XS Rating Curve= 0 ,0
Exp/Cntr=0.3,0.1

Type RM Length L Ch R = 1 ,4185    ,133.5,132.2,125.4
XS GIS Cut Line= 4
2175380.15712731615443.4404593082175602.20529176615384.681195734
2175737.30406925615387.7287202342175918.65529547615375.819414411
#Sta/Elev= 30
       0 2426.03      15  2420.7    33.1 2417.04    74.5 2405.88   103.3 2400.69
   165.5 2396.55   194.5 2392.63     211 2389.54   223.5 2389.43   247.7 2391.24
     268 2389.21   287.7 2389.88   299.12387.392   303.7 2387.25   311.7 2387.64
   316.42389.377   319.7 2391.93   335.7 2408.63   339.7 2411.95   343.7 2413.44
   355.7 2420.28   363.7 2423.03   390.9 2435.57   459.9 2461.07   467.9 2464.64
     496 2474.28     516  2482.3     528 2488.02   540.1 2489.91   546.6 2493.61
#Mann= 3 ,-1,0
       0      .1       0   299.1    .045       0   316.4      .1       0
#XS Ineff= 2 , 0
          248.09    2399
Permanent Ineff=
       F       F
Bank Sta=299.1,316.4
XS Rating Curve= 0 ,0
Exp/Cntr(USF)=0,0
Exp/Cntr=0.3,0.1

Type RM Length L Ch R = 1 ,4053    ,221.4,228,237.1
XS GIS Cut Line= 4
2175486.15840515615548.2550834532175641.16257633615512.777340001
2175715.87657744615465.5268799752175924.61592076615454.569537953
#Sta/Elev= 30
       0 2412.91    51.3 2405.64    96.4 2397.48   124.5 2393.48   133.4  2390.1
   145.7 2390.71     158 2384.67   163.8 2382.92   180.7 2382.09  185.022382.904
   189.9  2383.7   205.2 2382.74   219.4 2385.69   233.6 2383.53   238.3 2383.65
   242.1 2384.95   259.7 2395.35   271.7 2403.39   283.8 2409.11   315.8 2432.82
   323.8 2435.56   339.8 2445.62   347.9 2447.51   371.9 2459.97   387.9 2465.63
   399.5 2470.98   407.9 2473.54   424.9 2481.66     440 2486.99   456.4 2494.06
#Mann= 3 ,-1,0
       0      .1       0   163.8    .045       0  185.02      .1       0
Bank Sta=163.8,185.02
XS Rating Curve= 0 ,0
Exp/Cntr=0.3,0.1

Type RM Length L Ch R = 1 ,3825    ,172.8,172,170.5
XS GIS Cut Line= 4
2175526.70390025615638.1518632972175695.23060323615686.546357123
2175764.28824332615695.0844776132175945.84542177615673.911257453
#Sta/Elev= 30
       0 2402.21      39 2398.14    58.6 2395.05   105.6 2391.13   113.9 2389.97
   126.4 2385.69   130.5 2385.16     143 2386.04   151.4  2383.4   172.2 2381.02
   180.3 2378.43  192.342375.864   196.4 2375.25   212.6 2375.15  218.562375.864
   228.7 2377.89   236.7 2378.12   244.8 2379.61   257.4 2385.32     261 2387.35
     269 2394.86     277 2400.64   301.2 2415.87   317.3 2429.03   321.3 2431.36
   333.4  2436.5   349.5 2448.54   409.9 2475.84     422 2482.13   427.7 2484.12
#Mann= 3 ,-1,0
       0      .1       0  192.34    .045       0  218.56      .1       0
Bank Sta=192.34,218.56
XS Rating Curve= 0 ,0
Exp/Cntr=0.3,0.1

Type RM Length L Ch R = 1 ,3653    ,250.1,242.2,230.7
XS GIS Cut Line= 4
2175477.21821618615842.0762631592175638.63245308615856.984138277
 2175766.9382691615855.2198134552175970.55130446615814.139682237
#Sta/Elev= 30
       0 2405.54    27.1 2398.52    71.3 2383.72   103.4 2380.46   119.5 2382.08
   131.5 2381.31   155.6 2377.72   167.6 2374.13   191.6 2370.67  198.23 2368.34
   207.6 2367.54   218.7 2368.34   227.6 2370.32   236.9 2370.64   247.7 2370.19
   259.7 2368.04   267.7 2369.02   275.7 2368.43   291.7 2371.19   324.3 2395.27
   336.6 2400.41   355.8 2412.33   365.1 2415.22   381.5 2422.62   397.8 2431.52
     410 2435.83   430.4 2447.14   442.8 2450.92   483.6 2472.01   498.1 2477.35
#Mann= 3 ,-1,0
       0      .1       0  198.23    .045       0   218.7      .1       0
#XS Ineff= 2 , 0
                          277.78          2392.3
Permanent Ineff=
       F       F
Bank Sta=198.23,218.7
XS Rating Curve= 0 ,0
Exp/Cntr=0.3,0.1

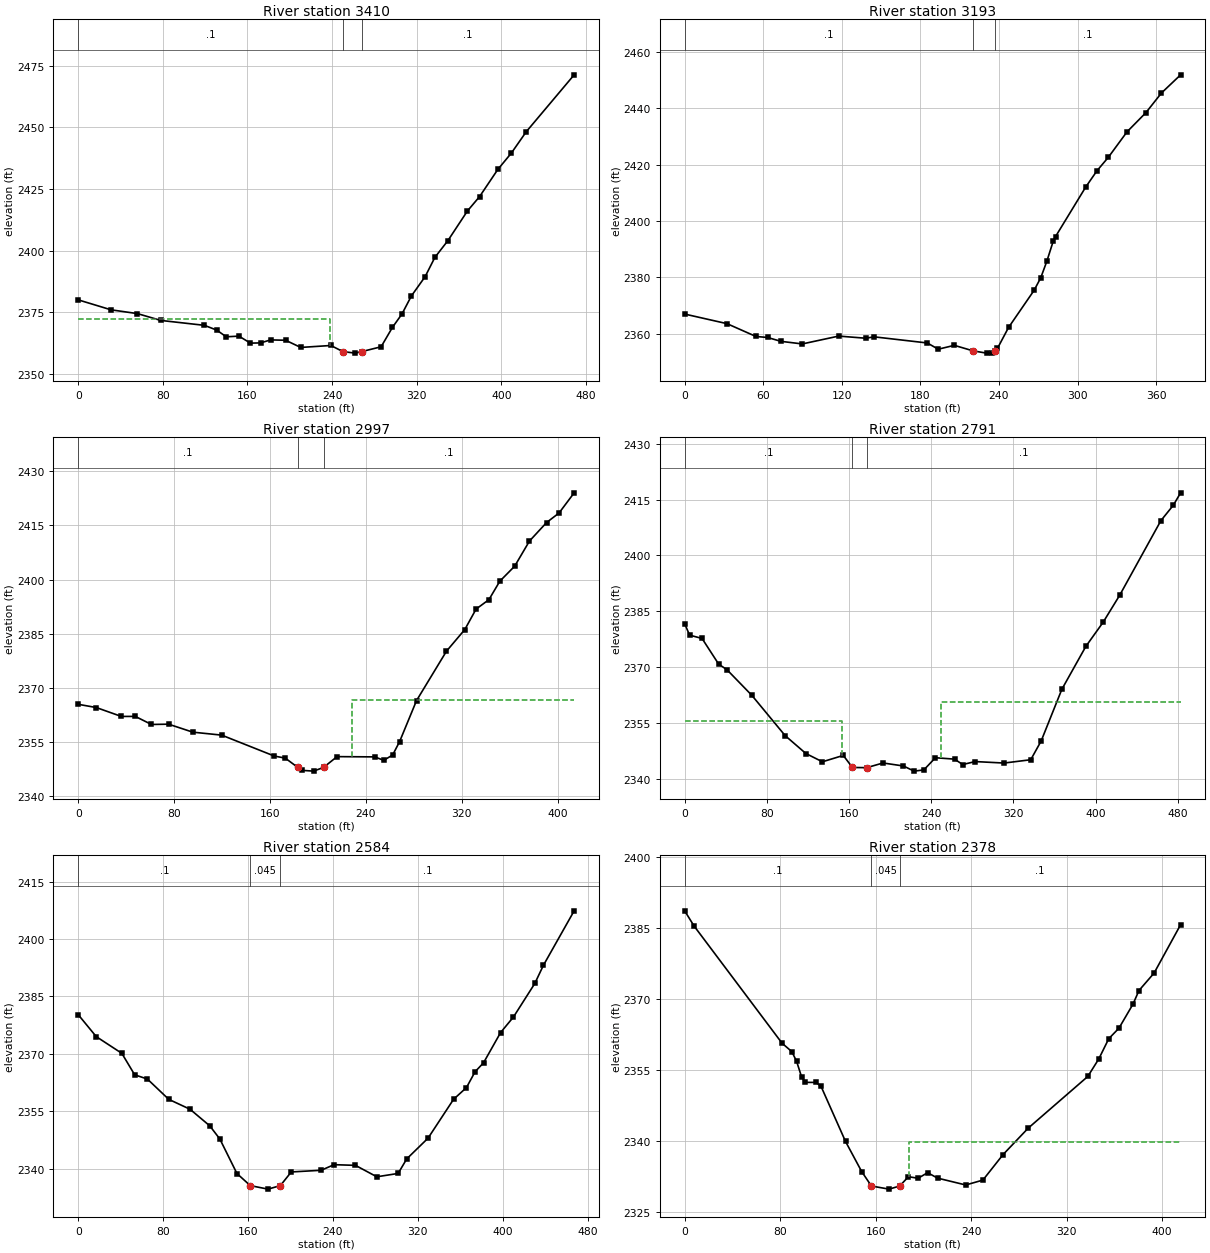
Type RM Length L Ch R = 1 ,3410    ,208.5,217.8,221.8
XS GIS Cut Line= 4
2175635.27052439616186.5119888252175772.02706921616110.598312462
2175842.99986799  615999.80400982176011.31582568615933.526426027
#Sta/Elev= 30
       0 2379.98    31.1 2375.93    55.9 2374.41    78.1 2371.63   119.3 2369.64
   131.1 2367.68   139.9 2364.99     152 2365.25   162.8 2362.42   172.4 2362.51
   181.9 2363.73   196.1 2363.58   210.4 2360.67   238.9 2361.46   250.2 2358.99
   261.8 2358.36   267.9 2358.96   286.4 2360.94   297.1 2368.82   306.1 2374.24
     315 2381.56     328  2389.4   337.2  2397.2   349.5    2404     368 2416.06
   379.5  2421.9   396.7 2432.89   409.6 2439.59   423.6 2448.21   468.9 2471.31
#Mann= 3 ,-1,0
       0      .1       0   250.2    .045       0   267.9      .1       0
#XS Ineff= 2 , 0
          237.92 2372.01
Permanent Ineff=
       F       F
Bank Sta=250.2,267.9
XS Rating Curve= 0 ,0
Exp/Cntr=0.3,0.1

Type RM Length L Ch R = 1 ,3193    ,199.7,195.6,192.2
XS GIS Cut Line= 4
2175735.05035825616276.7360643732175879.76924011616207.913508751
2175962.57618535616188.2942718642176072.11145662616112.299329721
#Sta/Elev= 30
       0 2367.01    32.3 2363.61    54.4 2359.07    63.3 2358.71    73.5 2357.34
    89.8 2356.42   117.6  2359.2   138.4 2358.44   144.6 2358.94   185.3 2356.76
   193.6 2354.55   205.9 2355.92  220.182353.968   230.5 2353.16   234.7 2353.21
  236.71 2353.97   238.8 2354.81   247.3 2362.25   266.8 2375.42   271.9 2379.87
   276.5 2385.68   281.4 2392.81   283.2 2394.49   306.2 2412.02   314.8  2417.8
   323.5 2422.59   337.8 2431.63   352.2 2438.42   364.1  2445.4   378.7 2451.83
#Mann= 3 ,-1,0
       0      .1       0  220.18    .045       0  236.71      .1       0
Bank Sta=220.18,236.71
XS Rating Curve= 0 ,0
Exp/Cntr=0.3,0.1

Type RM Length L Ch R = 1 ,2997    ,208.9,206.2,202.7
XS GIS Cut Line= 4
2175795.28553228 616458.171099522175938.19018367616407.960401232
2176033.18428766 616348.629241692176121.28706878616226.928396317
#Sta/Elev= 30
       0 2365.49    15.1 2364.59      36 2362.13    47.6 2362.14    61.1 2359.91
    75.4 2359.99    95.6 2357.78   119.7 2356.96   163.6 2351.17   172.7  2350.6
  183.212348.019   186.9 2347.21   196.3    2347  204.622348.017   215.9 2351.01
   247.3 2350.94   254.9 2349.99   262.3 2351.47   268.1 2355.17   282.2 2366.51
   307.2 2380.19   322.5 2386.18   331.9 2391.84   342.6 2394.44   351.7 2399.55
   364.1 2403.71   376.4 2410.65   390.7 2415.78   401.1 2418.42   413.7    2424
#Mann= 3 ,-1,0
       0      .1       0  183.21    .045       0  204.62      .1       0
#XS Ineff= 2 , 0
                           228.6         2366.65
Permanent Ineff=
       F       F
Bank Sta=183.21,204.62
XS Rating Curve= 0 ,0
Exp/Cntr=0.3,0.1

Type RM Length L Ch R = 1 ,2791    ,201.7,206.6,202.1
XS GIS Cut Line= 4
2176074.48982189616709.8954889612176097.60628205616552.540204919
2176159.14676317 616469.242120622176180.46194826616250.117605701
#Sta/Elev= 30
       0 2381.65     4.8 2378.59    16.9  2377.7    33.1  2370.8    41.2 2369.29
    65.4 2362.41    97.8 2351.59     118 2346.78   134.1 2344.56   154.4 2346.27
   163.3 2343.03  177.252342.982   193.1 2344.24     213 2343.43   223.3 2342.05
   232.8 2342.37   244.1 2345.65   262.7 2345.27   270.7 2343.82   282.8 2344.62
   310.9 2344.22   336.9 2345.11   347.1 2350.19   367.2 2364.05   390.6 2375.59
   407.4 2382.07   423.4 2389.27   463.6 2409.36   475.7  2413.5   482.8 2416.83
#Mann= 3 ,-1,0
       0      .1       0   163.3    .045       0  177.25      .1       0
#XS Ineff= 2 , 0
          153.07 2355.59  249.46         2360.69
Permanent Ineff=
       F       F
Bank Sta=163.3,177.25
XS Rating Curve= 0 ,0
Exp/Cntr=0.3,0.1

Type RM Length L Ch R = 1 ,2584    ,207.8,206.4,204.3
XS GIS Cut Line= 4
2176274.73594352616734.1297924642176287.54404353616588.116174534
  2176311.546896616508.5891666272176338.28193637616272.311675191
#Sta/Elev= 30
       0 2380.26      17 2374.53    41.1 2370.17    53.2 2364.57    65.2 2363.46
    85.3 2358.17   105.4 2355.58     124 2351.25   133.5 2347.81   149.6 2338.81
  162.182335.656   178.9 2334.74  190.512335.657   200.8 2339.22     229 2339.66
   241.1 2341.12   261.3 2340.94   281.4 2337.96   301.5 2338.83   309.6 2342.62
   329.7 2348.04   353.8 2358.19   365.9 2361.23     374 2365.36     382  2367.7
   398.1  2375.6   410.2 2379.65   430.3 2388.39   438.4 2393.12   467.4 2407.35
#Mann= 3 ,-1,0
       0      .1       0  162.18    .045       0  190.51      .1       0
Bank Sta=162.18,190.51
XS Rating Curve= 0 ,0
Exp/Cntr=0.3,0.1

Type RM Length L Ch R = 1 ,2378    ,199.9,206,210.3
XS GIS Cut Line= 4
2176459.29733468 616776.828308492176490.62173955616634.714603142
2176499.47315253616572.5664082352176565.78197841 616376.14237138
#Sta/Elev= 30
       0 2388.69     7.8  2385.5    81.6 2360.68    89.8 2358.89    93.8 2356.84
    97.9 2353.59   101.1 2352.39   110.2 2352.38   114.3 2351.53   134.8 2339.88
   148.3 2333.53  156.482330.457   171.3  2329.8  180.192330.457   187.5 2332.43
   195.6  2332.1   203.6 2333.28   211.9 2332.13   235.5 2330.68   249.9 2331.71
   266.8 2337.11   287.9 2342.71   337.8 2353.64     347 2357.34   355.4 2361.64
   363.9 2363.85   375.7 2368.95   380.7 2371.83   393.4 2375.53   415.6 2385.76
#Mann= 3 ,-1,0
       0      .1       0  156.48    .045       0  180.19      .1       0
#XS Ineff= 2 , 0
                          187.67         2339.74
Permanent Ineff=
       F       F
Bank Sta=156.48,180.19
XS Rating Curve= 0 ,0
Exp/Cntr=0.3,0.1