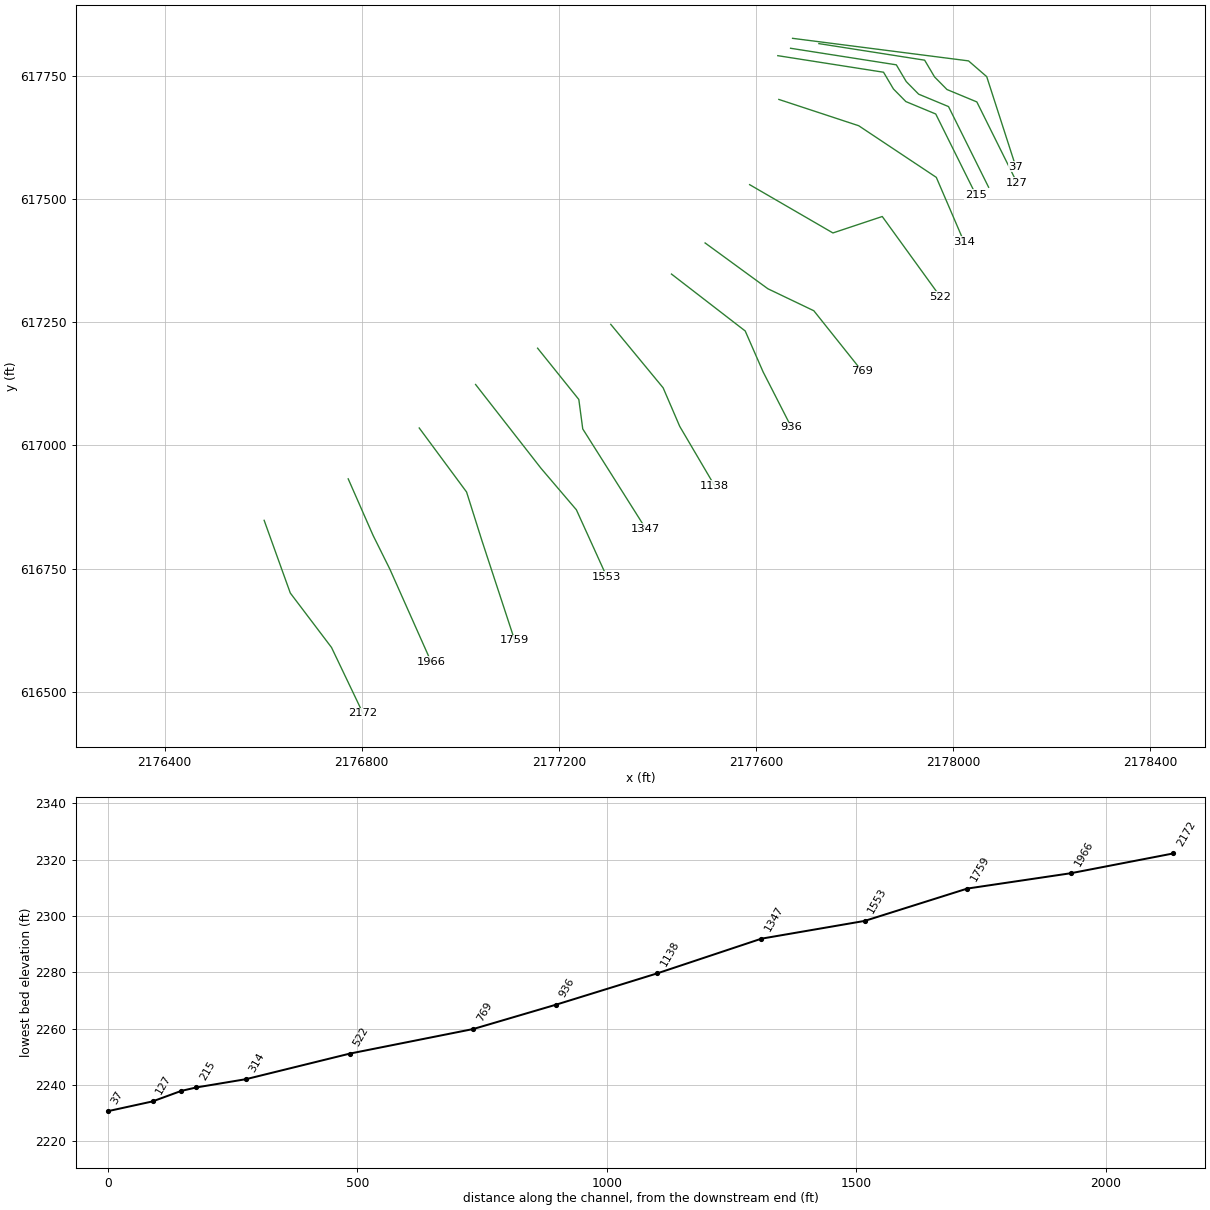
HEC-RAS study DEVILFK.prj: DEVILFK

--- DEVILFK.g01 (geometry) --- (continued)

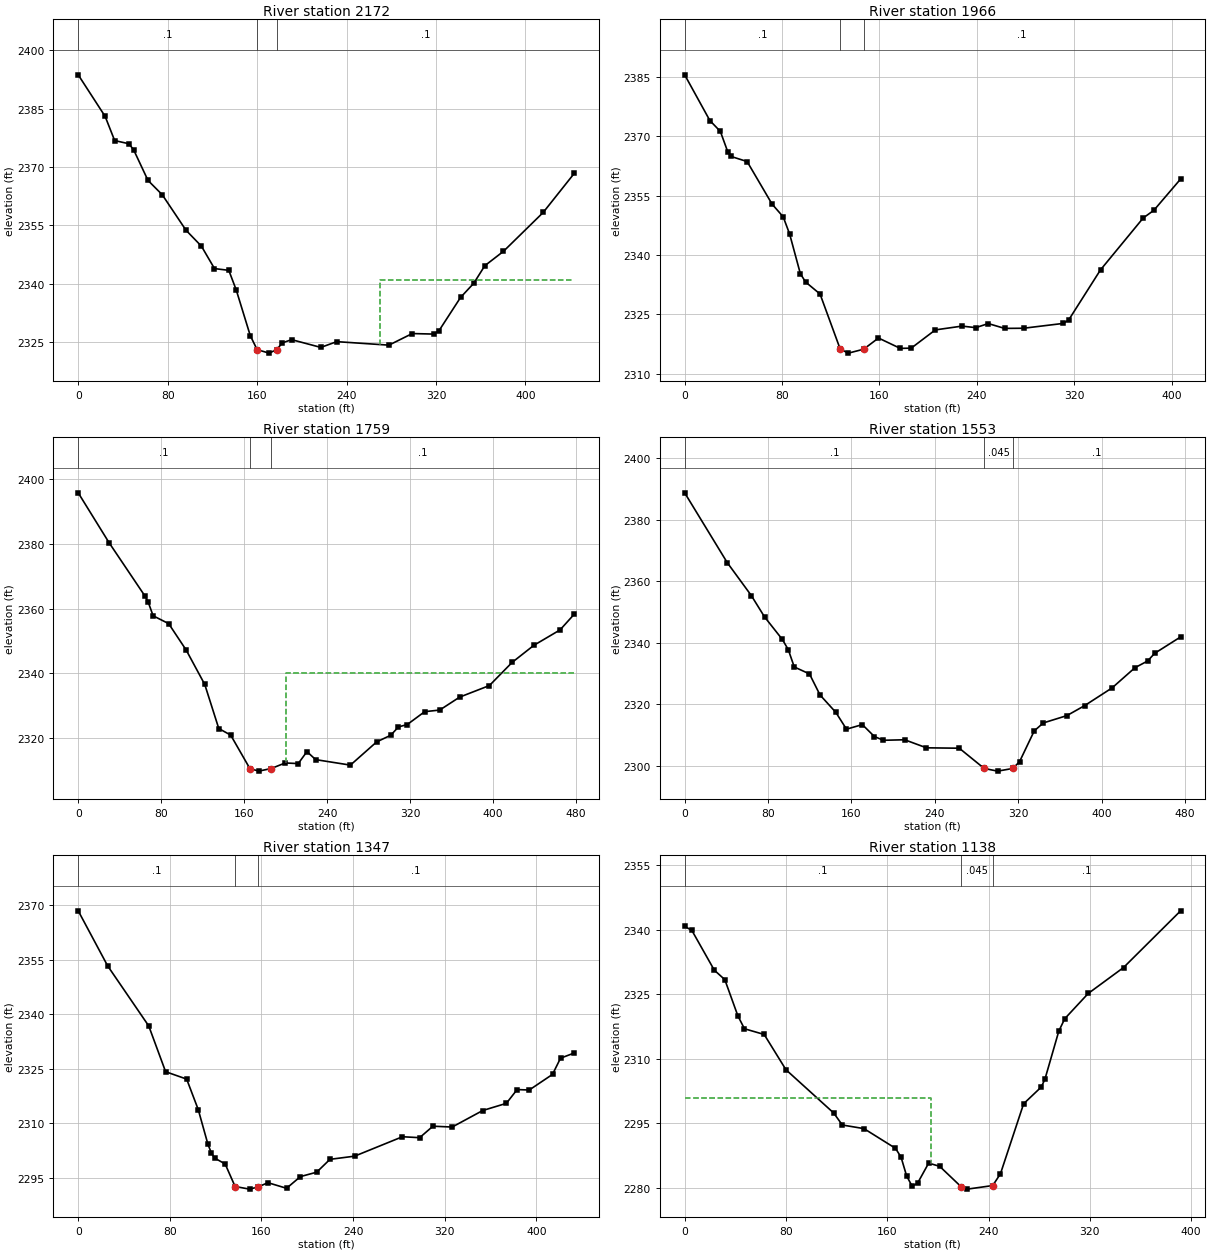
Type RM Length L Ch R = 1 ,2172    ,206.5,205.4,202.8
XS GIS Cut Line= 4
2176601.96671202616847.900984243 2176655.0166141 616700.40728959
2176738.65801294616589.9456196952176802.59805938616456.187902145
#Sta/Elev= 30
       0  2393.7    24.1 2383.01    32.6 2376.81    45.4 2375.99    49.7 2374.36
    62.4 2366.58    75.2 2362.88    96.4 2353.78   110.2 2349.68   121.9 2343.92
   134.7 2343.47   141.4 2338.38   153.9  2326.7  160.032323.092   170.8  2322.2
  177.412323.093   182.7 2324.85   190.9 2325.66     217 2323.67   231.3 2325.15
   277.9 2324.25   298.8 2327.23   318.3 2327.09   322.8    2328     342 2336.51
   353.8 2340.15   363.7 2344.66   380.4 2348.36   415.9 2358.34   443.6 2368.35
#Mann= 3 ,-1,0
       0      .1       0  160.03    .045       0  177.41      .1       0
#XS Ineff= 2 , 0
                          269.58         2341.11
Permanent Ineff=
       F       F
Bank Sta=160.03,177.41
XS Rating Curve= 0 ,0
Exp/Cntr=0.3,0.1

Type RM Length L Ch R = 1 ,1966    ,209.2,207.5,206.1
XS GIS Cut Line= 4
2176772.50975176616932.1202936352176822.94917411616817.442059811
2176856.98921364 616748.985720842176940.68680342616561.085837608
#Sta/Elev= 30
       0 2385.51    20.7 2373.95    29.3 2371.21    35.4 2366.04    38.2 2364.87
    51.3 2363.59    71.8 2352.83    80.9 2349.63    86.2 2345.29      95 2335.27
    99.3 2333.15   111.2 2330.11  127.792316.162   134.5 2315.17  147.032316.164
   159.2 2318.99   177.1 2316.37   186.1 2316.43   205.9 2321.04   227.8    2322
   239.1 2321.61   249.4 2322.64   262.8 2321.42   278.4 2321.46     311 2322.68
   315.4 2323.53   341.6 2336.22   376.7 2349.34   385.4 2351.26   407.4 2359.18
#Mann= 3 ,-1,0
       0      .1       0  127.79    .045       0  147.03      .1       0
Bank Sta=127.79,147.03
XS Rating Curve= 0 ,0
Exp/Cntr=0.3,0.1

Type RM Length L Ch R = 1 ,1759    ,202.8,205.5,216.5
XS GIS Cut Line= 4
2176916.68062592617035.2619602182177012.73164393616905.347771412
2177043.92506433616806.5537355282177110.41105661616604.236592258
#Sta/Elev= 30
       0  2395.8    29.7  2380.4      64 2364.04    67.3 2362.16    72.2 2357.77
    87.2 2355.34   104.1 2347.16     122 2336.52   135.5  2322.9     147 2320.86
  165.462310.528     174 2309.72  186.082310.528   199.5 2312.25   212.1 2312.05
   220.5 2315.76   228.9 2313.28   262.4 2311.58   287.7 2318.76   301.3 2320.82
   308.7 2323.39   317.2 2324.13     334 2328.11   348.5 2328.61   367.7 2332.61
   396.4 2336.19   418.2 2343.32   439.2 2348.62   464.5  2353.4   478.1 2358.23
#Mann= 3 ,-1,0
       0      .1       0  165.46    .045       0  186.08      .1       0
#XS Ineff= 2 , 0
                             200            2340
Permanent Ineff=
       F       F
Bank Sta=165.46,186.08
XS Rating Curve= 0 ,0
Exp/Cntr=0.3,0.1

Type RM Length L Ch R = 1 ,1553    ,213.7,207,209.6
XS GIS Cut Line= 4
2177031.01602782617123.5364587642177163.76176743 616953.46913613
 2177235.5308716 616869.25748878  2177297.296723616733.319311623
#Sta/Elev= 30
       0 2388.73    40.9    2366    63.9 2355.34    76.6 2348.39    93.7 2341.05
    99.4 2337.72   105.1 2332.11   119.7 2329.85   129.8 2323.01     145 2317.34
   155.2 2311.88   170.4 2313.37     182 2309.48   190.7 2308.27     211 2308.44
   231.9 2305.82   263.4 2305.69   287.32299.108   300.2 2298.24  314.742299.108
   321.2 2301.31   335.3 2311.32     344 2313.91   366.6 2316.29   383.6 2319.53
     410 2325.31   431.9 2331.87     444 2334.04   450.8 2336.54   475.7 2341.88
#Mann= 3 ,-1,0
       0      .1       0   287.3    .045       0  314.74      .1       0
Bank Sta=287.3,314.74
XS Rating Curve= 0 ,0
Exp/Cntr=0.3,0.1

Type RM Length L Ch R = 1 ,1347    ,203,208.3,211
XS GIS Cut Line= 4
2177156.88331842617197.1843134692177240.48179704617093.154956177
2177248.45668684617033.4074940822177376.23745462616831.085779718
#Sta/Elev= 30
       0 2368.53    25.7 2353.38    61.6 2336.83    76.3 2324.25    94.7 2322.21
   104.8 2313.82   113.3 2304.22   116.2 2301.94     119  2300.5   128.3 2298.85
  136.982292.648   149.6 2291.93  156.682292.494   165.7  2293.7   181.9 2292.16
     194 2295.38   208.2 2296.59   219.8 2300.13   241.3    2301   283.1 2306.35
   298.1 2306.09   309.7 2309.25   326.5 2309.02   353.2 2313.57   373.8 2315.54
   383.2 2319.33   393.8 2319.21   414.1 2323.51   421.1 2327.97     433 2329.39
#Mann= 3 ,-1,0
       0      .1       0  136.98    .045       0  156.68      .1       0
Bank Sta=136.98,156.68
XS Rating Curve= 0 ,0
Exp/Cntr=0.3,0.1

Type RM Length L Ch R = 1 ,1138    ,202,202.5,202.7
XS GIS Cut Line= 4
2177305.28742809617245.613915254 2177411.6104315617116.734935115
 2177445.2102107 617038.62023239 2177515.9792677616918.256533014
#Sta/Elev= 30
       0 2340.75     5.7 2339.78    23.4 2330.55    31.7 2328.35      42 2319.94
    47.2 2316.93    62.8  2315.6      80  2307.4   117.7 2297.34   124.5 2294.55
   141.6 2293.71   166.5 2289.13   170.9 2287.07   175.3  2282.7   179.7 2280.29
     184 2281.05   192.7 2285.69   201.4 2284.94218.35832280.191   223.2 2279.64
   243.3 2280.47   249.4 2283.21   267.7 2299.49   281.6 2303.37   284.5 2305.17
   295.5 2316.39   300.2 2319.27   318.7 2325.13   346.6 2331.16   391.7 2344.35
#Mann= 3 ,-1,0
       0      .1       0218.3583    .045       0   243.3      .1       0
#XS Ineff= 2 , 0
          194.37 2300.76
Permanent Ineff=
       F       F
Bank Sta=218.3583,243.3
XS Rating Curve= 0 ,0
Exp/Cntr=0.3,0.1

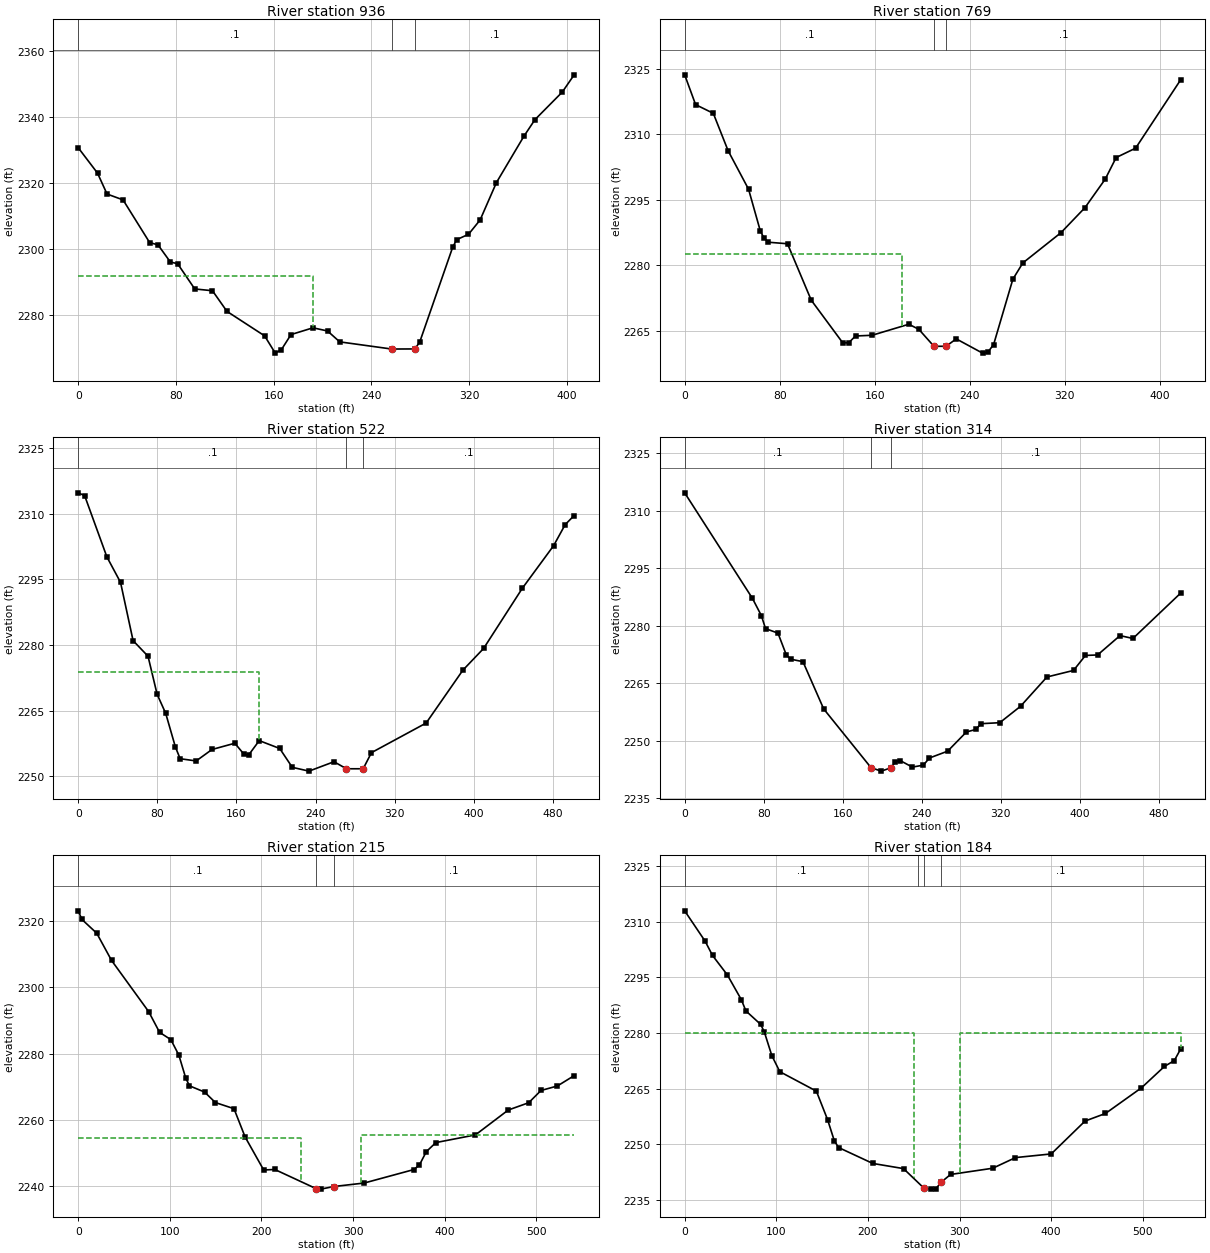
Type RM Length L Ch R = 1 ,936     ,159.6,166.4,173.6
XS GIS Cut Line= 4
2177428.50473579617347.6171033622177578.12920808 617232.12475949
 2177614.3525155617149.2796846622177671.97104692 617036.54684144
#Sta/Elev= 30
       0 2330.75    15.8 2323.06    23.6 2316.72    36.7 2314.95    58.5 2302.01
    65.3 2301.33    75.4 2296.15    81.4  2295.6    95.4 2287.97   109.9 2287.43
   121.8 2281.17   152.6 2273.76   161.3 2268.53   166.3 2269.56   174.2 2274.15
   192.2  2276.2   204.1 2275.24   214.1 2271.94   256.6 2269.77  275.52  2269.8
   279.5 2271.81   306.5 2300.54   309.8  2302.9   319.5 2304.52     329 2308.86
   342.4 2320.21   364.9 2334.25   373.9 2339.25   396.3 2347.62     406 2352.83
#Mann= 3 ,-1,0
       0      .1       0   256.6    .045       0  275.52      .1       0
#XS Ineff= 2 , 0
          192.42  2291.9
Permanent Ineff=
       F       F
Bank Sta=256.6,275.52
XS Rating Curve= 0 ,0
Exp/Cntr=0.3,0.1

Type RM Length L Ch R = 1 ,769     ,241.9,247.1,256.7
XS GIS Cut Line= 4
2177496.73067835617410.7508179372177624.00930178 617317.85646117
2177717.32688097617273.2087228662177815.00923109617150.749029238
#Sta/Elev= 30
       0 2323.65     9.2 2316.82    24.1 2314.83    36.6 2306.24    53.8 2297.43
    63.7 2287.87    66.6 2286.34    70.5 2285.28    86.6 2284.93   106.6 2271.99
     133 2262.27     138  2262.2   143.9 2263.79   157.8 2263.95   188.8 2266.48
   197.2 2265.32  209.962261.421  220.222261.435   228.7 2263.13   250.9 2259.86
   255.3 2260.06   260.2 2261.83   276.4  2276.8   284.8 2280.53   316.9 2287.46
   337.1 2293.19   354.2 2299.74   363.4 2304.69   379.8 2306.84   417.7 2322.49
#Mann= 3 ,-1,0
       0      .1       0  209.96    .045       0  220.22      .1       0
#XS Ineff= 2 , 0
          183.03 2282.55
Permanent Ineff=
       F       F
Bank Sta=209.96,220.22
XS Rating Curve= 0 ,0
Exp/Cntr=0.3,0.1

Type RM Length L Ch R = 1 ,522     ,215.6,208.1,197.5
XS GIS Cut Line= 4
2177587.11861993617529.0352865412177756.09096172617431.056021011
2177856.20062002617464.4239510932177973.89518193617301.819868398
#Sta/Elev= 30
       0 2314.81     6.5 2314.17      29 2300.15    42.8 2294.33    55.5 2280.99
    70.6 2277.43    79.8 2268.72    88.5 2264.35    98.3 2256.66   103.1 2253.98
   119.3 2253.47   135.3 2256.09   158.4 2257.52   167.7 2254.99   172.3 2254.81
   183.1 2258.12   203.8 2256.32   216.5 2252.01   233.4 2251.14   258.7 2253.29
   271.3 2251.68   288.2 2251.68   296.6 2255.37   351.9 2262.14   389.1 2274.25
     410  2279.2   449.2 2292.98   480.8 2302.71   492.5 2307.53   501.6 2309.62
#Mann= 3 ,-1,0
       0      .1       0   271.3    .045       0   288.2      .1       0
#XS Ineff= 2 , 0
          182.38 2273.78
Permanent Ineff=
       F       F
Bank Sta=271.3,288.2
XS Rating Curve= 0 ,0
Exp/Cntr=0.3,0.1

Type RM Length L Ch R = 1 ,314     ,100.7,99.5,95.9
XS GIS Cut Line= 4
2177646.39874638617701.967357555 2177808.4133848617648.613139282
2177965.87339482617543.8566863312178022.27404966617412.776907476
#Sta/Elev= 30
       0 2314.69    68.6 2287.16    77.7 2282.64    81.9 2279.25    94.5 2278.08
   102.9 2272.43   107.2 2271.28   119.8 2270.63   140.8  2258.3   188.82242.956
   199.1 2242.06  209.322242.955   213.5 2244.54   218.3 2244.82   230.6 2243.11
   241.8 2243.62   247.9 2245.48   266.4 2247.27   285.4 2252.28   295.2 2252.95
     300 2254.44   319.2  2254.7   340.2 2258.98     367 2266.63   393.9 2268.34
     406 2272.25   418.3 2272.38     441 2277.43   454.1 2276.68   502.4 2288.51
#Mann= 3 ,-1,0
       0      .1       0   188.8    .045       0  209.32      .1       0
Bank Sta=188.8,209.32
XS Rating Curve= 0 ,0
Exp/Cntr(USF)=0,0
Exp/Cntr=0.3,0.1

Type RM Length L Ch R = 1 ,215     ,30.5,30.5,30.7
BEGIN DESCRIPTION:
structure
END DESCRIPTION:
XS GIS Cut Line= 6
2177644.24312088617790.7649687372177858.81561036617757.166429461
2177878.90957954617723.1978808662177904.11038239617697.631848988
2177964.73840084617672.4310461372178046.08775117617508.727743677
#Sta/Elev= 30
       0 2323.06       4 2320.47    20.2 2316.31    36.4 2308.09    76.9 2292.65
    88.8 2286.41   101.1 2284.21   109.8 2279.55   117.3 2272.65   121.4 2270.28
   137.9  2268.4   149.7 2265.23     170 2263.38   182.1 2254.87   202.4 2244.89
   214.5 2245.05   259.9 2239.23   264.8 2239.12   278.62239.893   312.1 2240.96
   366.5 2245.04   372.4 2246.44   379.9 2250.43   390.3 2253.16   433.5 2255.48
   469.3 2262.98   491.6 2265.18     505 2268.87   522.9 2270.23   541.2 2273.35
#Mann= 3 ,-1,0
       0      .1       0   259.9    .045       0   278.6      .1       0
#XS Ineff= 2 , 0
          242.62 2254.51   308.2         2255.46
Permanent Ineff=
       F       F
Bank Sta=259.9,278.6
XS Rating Curve= 0 ,0
Exp/Cntr(USF)=0,0
Exp/Cntr=0.3,0.1

Type RM Length L Ch R = 1 ,184     ,56.1,57.3,58.7
BEGIN DESCRIPTION:
structure
END DESCRIPTION:
XS GIS Cut Line= 6
2177670.17635067617805.7959787422177884.74884015617772.197439466
2177904.84280933617738.2288908722177930.04361218617712.662858994
2177990.67163063617687.4620561432178072.02098096617523.758753682
#Sta/Elev= 30
       0 2312.99    22.3  2304.8    30.4 2300.94    46.6 2295.68    61.8 2289.02
    66.8 2285.98      83 2282.32      87 2280.23    95.1 2273.92   103.8 2269.58
   143.7 2264.33   155.9 2256.66   163.3 2250.92     168  2249.1   205.3 2244.81
   238.8 2243.42   261.12238.145   268.8 2237.88     274 2237.97   280.22239.816
   290.2 2241.84   336.2 2243.52     361 2246.39     400 2247.38   436.9 2256.25
   459.2  2258.3   498.5 2265.23   523.6 2271.01   534.3 2272.57   541.2 2275.68
#Mann= 4 ,-1,0
       0      .1       0  254.83     .07       0   261.1    .045       0
   280.2      .1       0
#XS Ineff= 2 , 0
             250    2280     300            2280
Permanent Ineff=
       F       F
Bank Sta=261.1,280.2
XS Rating Curve= 0 ,0
Exp/Cntr(USF)=0,0
Exp/Cntr=0.3,0.1

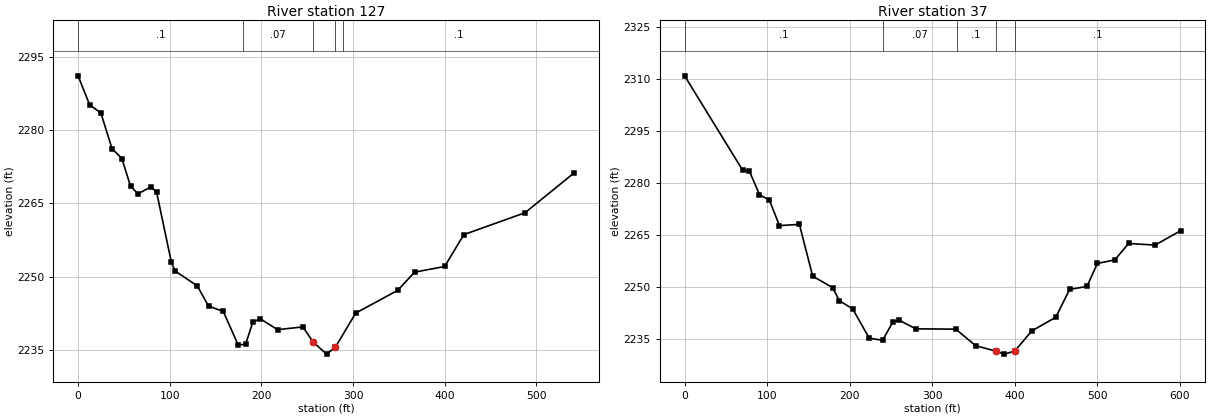
Type RM Length L Ch R = 1 ,127     ,87.5,90,89.9
BEGIN DESCRIPTION:
structure
END DESCRIPTION:
XS GIS Cut Line= 6
  2177727.647615617815.2369460532177942.22010448617781.638406778
2177962.31407366617747.6698581832177987.51487651617722.103826305
2178048.14289496617696.9030234542178129.49224529617533.199720994
#Sta/Elev= 30
       0 2291.12    12.7 2285.13    24.8 2283.57      37 2276.22    47.8 2274.19
    57.2 2268.55    65.3 2266.97    79.3 2268.37    85.6 2267.37   101.8 2252.94
   105.8 2251.18   130.1 2248.12   142.3    2244   158.4  2242.9   174.6 2236.07
   182.7 2236.15   190.8 2240.78   198.9 2241.38   217.7 2239.17   245.3 2239.73
   256.52236.627   271.1 2234.16   280.72235.567   302.9 2242.56   348.8 2247.22
   367.2 2250.94     400  2252.1   420.9 2258.62   487.7  2263.1   541.2 2271.25
#Mann= 5 ,-1,0
       0      .1       0     180     .07       0   256.5    .045       0
   280.7     .07       0  289.22      .1       0
Bank Sta=256.5,280.7
XS Rating Curve= 0 ,0
Exp/Cntr(USF)=0,0
Exp/Cntr=0.3,0.1

Type RM Length L Ch R = 1 ,37      ,,,
XS GIS Cut Line= 4
2177674.23775309617825.9527902662178031.24725438 617780.20685398
2178068.19455017617748.166791168  2178127.286421617565.158033927
#Sta/Elev= 30
       0    2311    70.3 2283.76    78.6 2283.43    90.7 2276.73   102.8 2275.11
   114.9 2267.77   139.1 2268.11   155.2 2253.18   179.4 2249.86   187.5  2246.1
   203.6 2243.75   223.8 2235.26   239.9 2234.67   252.6 2240.05     260 2240.45
   280.2 2237.97   328.6 2237.88   352.7 2233.11   376.8 2231.56   387.6 2230.67
  400.112231.565   420.7 2237.37   449.8 2241.31   466.6 2249.37   487.6  2250.2
   500.2 2256.84   521.3 2257.87   538.1 2262.61   570.1 2262.14   601.1 2266.29
#Mann= 5 ,-1,0
       0      .1       0     240     .07       0     330      .1       0
   376.8    .045       0  400.11      .1       0
Bank Sta=376.8,400.11
XS Rating Curve= 0 ,0
Exp/Cntr(USF)=0,0
Exp/Cntr=0.3,0.1
LCMann Table=0

Chan Stop Cuts=-1
Use User Specified Reach Order=0
Composite Channel Slope=5